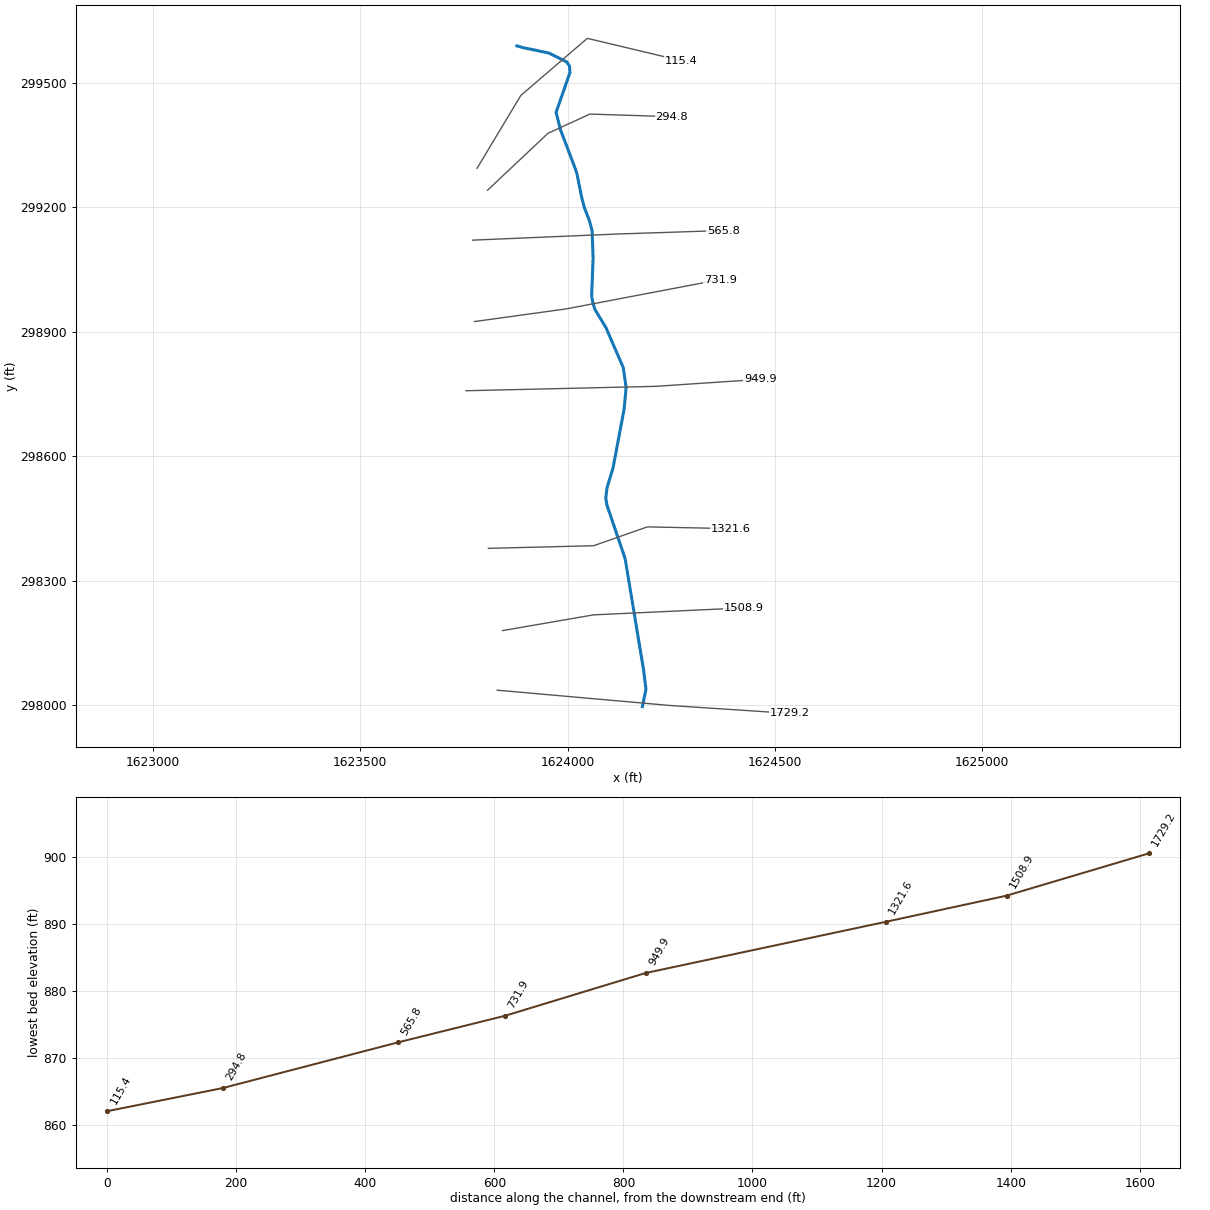
--- bbbybrnch.prj (project) ---

Proj Title=bbbybrnch
Current Plan=p01
Default Exp/Contr=0,0
English Units
Geom File=g01
Flow File=f01
Plan File=p01
BEGIN DESCRIPTION:
END DESCRIPTION:
DSS Export Rating Curves= 0
DSS Export Rating Curve Sorted= 0
DSS Export Volume Flow Curves= 0
DXF OffsetX= 0
DXF OffsetY= 0
DXF ScaleX= 0
DXF ScaleY= 0

--- bbbybrnch.p01 (plan) ---

Plan Title=Approximate Study - 100yr
Program Version=4.00
Geom File=g01
Flow File=f01
Subcritical Flow
K Sum by GR= 0
Std Step Tol= 0.01
Critical Tol= 0.01
Num of Std Step Trials= 20
Max Error Tol= 0.3
Flow Tol Ratio= 0.001
Split Flow NTrial= 30
Split Flow Tol= 0.02
Split Flow Ratio= 0.02
Log Output Level= 0
Friction Slope Method= 1
Unsteady Friction Slope Method= 2
Unsteady Bridges Friction Slope Method= 1
Parabolic Critical Depth
Global Vel Dist= 0 , 0 , 0
Global Log Level= 0
CheckData=True
Encroach Param=-1 ,0,0, 0
Run HTab= 0
Run UNet= 0
Run PostProcess= 0
Run WQNet= 0
UNET Theta= 0
UNET Theta Warmup= 0
UNET ZTol= 0
UNET ZSATol= 0
UNET MxIter= 0
UNET MaxInSteps= 0
UNET DtIC= 0
UNET DtMin= 0
UNET MaxCRTS= 0
UNET WFStab= 0
UNET SFStab= 0
UNET WFX= 1
UNET SFX= 1
UNET DSS MLevel= 1
UNET DZMax Abort= 0
UNET Convert EG Bridges= 0
UNET Use Existing IB Tables= 0
UNET Froude Reduction=False
UNET Froude Limit= 0
UNET Froude Power= 0
UNET Time Slicing=0,0, 5
Write IC File= 0
Echo Input=False
Echo Output=False
Write Detailed= 0
Detailed Automatic Start=False, 0
WQ ULTIMATE=-1
WQ Max Comp Step=1HOUR
WQ Output Interval=15MIN
WQ Output Selected Increments= 0
WQ Output face flow=0
WQ Output face velocity=0
WQ Output face area=0
WQ Output face dispersion=0
WQ Output cell volume=0
WQ Output cell surface area=0
WQ Output cell continuity=0
WQ Output face conc=0
WQ Output face dconc_dx=0
WQ Output face courant=0
WQ Output face peclet=0
WQ Output face adv mass=0
WQ Output face disp mass=0
WQ Output cell mass=0
WQ Output cell source sink temp=0
WQ Output cell source sink nsm=0
WQ Output MaxMinRange=-1
WQ Daily Max Min Mean=-1
WQ Daily Range=0
WQ Daily Time=0
WQ Create Restart=0
WQ Fixed Restart=0
WQ System Summary=False
Sorting and Armoring Iterations= 10
XS Update Threshold= 0.02
Hydraulics Update Threshold= 0.02
Energy Slope Method= 1
Volume Change Method= 0
XS Weighting Method= 0
Number of US Weighted Cross Sections= 1
Number of DS Weighted Cross Sections= 1
Upstream XS Weight=0.25
Main XS Weight=0.5
Downstream XS Weight=0.25
Number of DS XS's Weighted with US Boundary= 1
Upstream Boundary Weight= 1
Weight of XSs Associated with US Boundary= 0
Number of US XS's Weighted with DS Boundary= 1
Downstream Boundary Weight= 0.5
Weight of XSs Associated with DS Boundary= 0.5
Sediment Output Level= 4
Mass or Volume Output= 0
Output Increment Type= 1
Profile and TS Output Increment= 10
XS Output Flag= 0
XS Output Increment= 10
Disregard all LS=0
Disregard all Conn=0
Disregard all Breaches=0
Disregard all Pumps=0

--- bbbybrnch.f01 (steady flow) ---

Flow Title=USGS Regression Equation
Program Version=4.00
Number of Profiles=1
Profile Names=P100yr
River Rch & RM=bbbybrnch,Main      ,1729.2
     355
River Rch & RM=bbbybrnch,Main      ,294.8
     371
Boundary for River Rch & Prof#=bbbybrnch,Main      ,1
Up Type=0
Dn Type=3
Dn Slope=0.02286

--- bbbybrnch.g01 (geometry) ---

Geom Title=USGS 3m DEM
Program Version=4.00

River Reach=bbbybrnch       ,Main
Reach XY= 30
     1624180.432      297996.515     1624189.081      298038.069
     1624183.345      298085.332     1624138.798      298353.413
     1624094.886      298482.604     1624092.193      298499.121
     1624095.226      298524.051      1624109.69      298571.726
     1624136.405      298713.317      1624141.29      298765.571
     1624134.354      298813.705     1624092.824      298909.594
      1624065.84      298954.079      1624060.74      298971.726
      1624058.08      298987.083     1624061.655      299076.715
     1624059.359       299142.98     1624052.662      299168.218
     1624040.942      299198.343     1624034.562      299221.867
     1624022.911      299279.951     1624019.143      299291.965
     1623982.794      299387.666     1623972.477      299428.945
     1624006.022      299525.578     1624004.525      299540.981
     1623998.399      299550.339     1623955.333      299571.954
     1623893.414        299584.9     1623877.974      299589.311

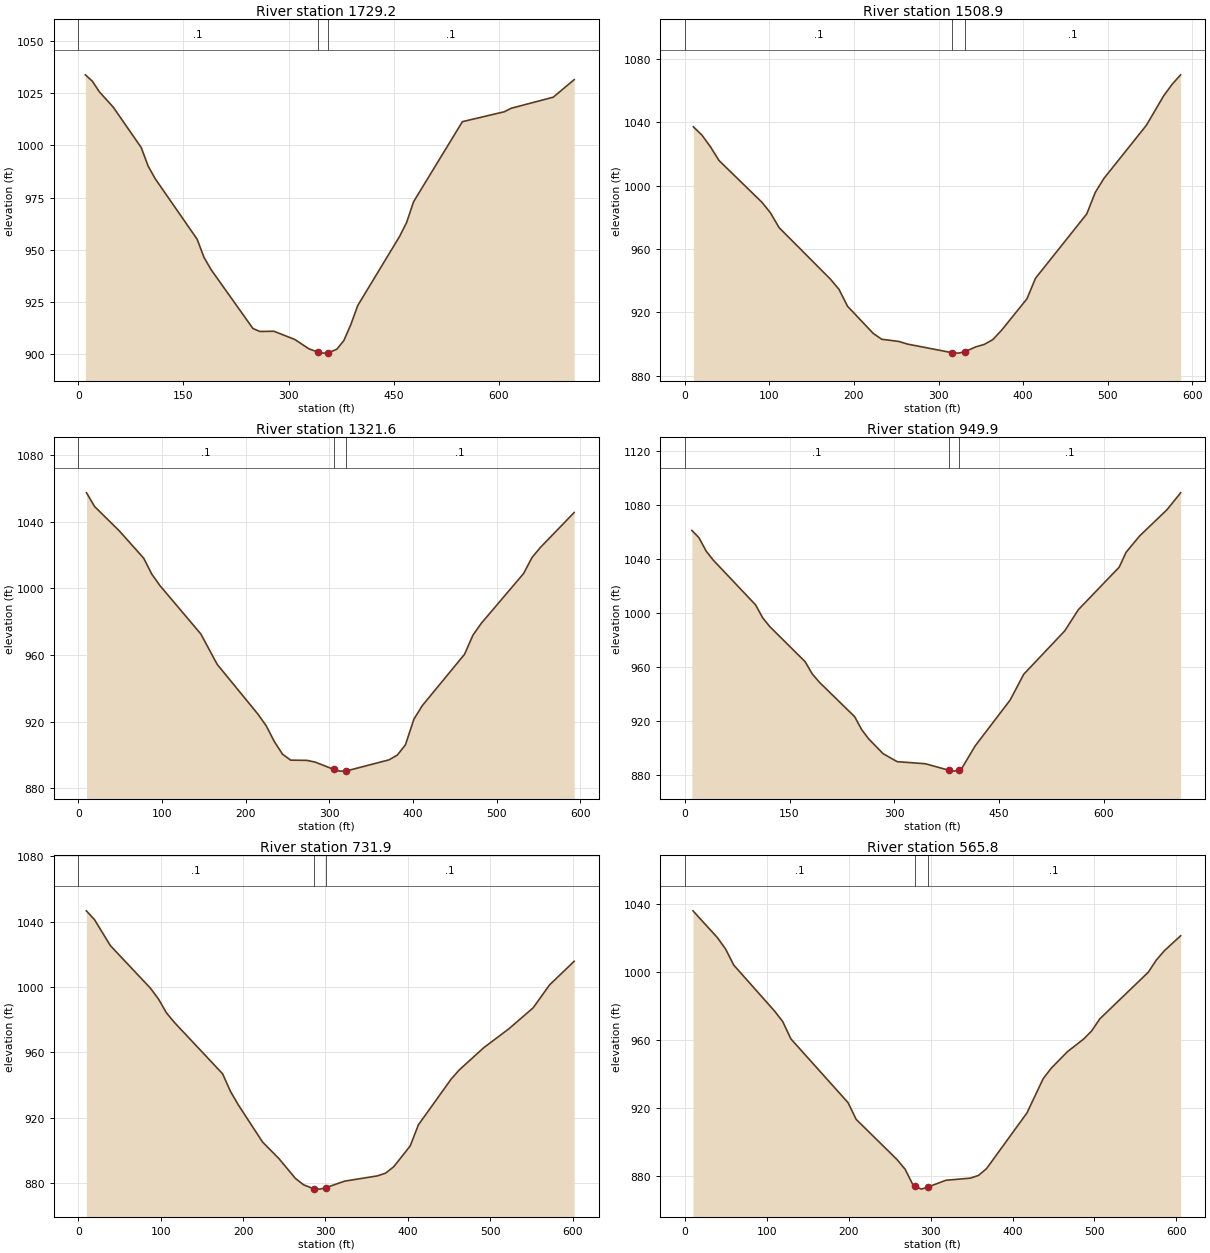
Type RM Length L Ch R = 1 ,1729.2  ,217.2,220.3,223.3
XS GIS Cut Line= 3
     1623830.336      298035.984     1624247.214      297999.046
     1624535.334      297980.049
#Sta/Elev= 30
      10 1033.76    19.9 1030.76    29.9 1025.68    49.8 1018.29    89.7  998.99
    99.6  990.09   109.6  984.09   169.4  955.14   179.4  946.34   189.3  940.59
   249.1  912.37   259.1  910.96     279  911.07   308.9  907.12   328.8  902.68
   341.3  901.13   348.8   900.6   356.3  900.69   368.7  902.46   378.7  906.58
   388.6  914.15   398.6  923.39   458.3  956.45   468.3  963.11   478.3  973.08
   547.9 1011.35   607.7 1016.09   617.6 1017.77   677.4 1023.05   707.3 1031.45
#Mann= 3 , 0 , 0
       0      .1       0   341.3    .045       0   356.3      .1       0
Bank Sta=341.3,356.3
XS Rating Curve= 0 ,0
Exp/Cntr=0.3,0.1

Type RM Length L Ch R = 1 ,1508.9  ,180.7,187.3,193.9
XS GIS Cut Line= 3
     1623843.001      298179.517     1624062.521      298217.511
     1624425.574      298234.397
#Sta/Elev= 30
    10.1 1037.23    20.3 1031.92    30.4 1024.53    40.5 1015.88    91.1  989.59
   101.3  982.86   111.4  973.58   172.2  940.97   182.3  934.55   192.4  923.88
   222.8   906.7   232.9  903.02   253.1  901.65   263.2  899.99   316.2  894.52
   323.7  894.27   331.2   895.2   343.9   898.2     354  899.75   364.1  902.81
   374.2  908.52   404.5  928.55   414.6  941.53   475.2  982.15   485.3  995.78
   495.4 1004.51   545.8 1038.22     566 1056.62   576.1 1064.01   586.2 1070.02
#Mann= 3 , 0 , 0
       0      .1       0   316.2    .045       0   331.2      .1       0
Bank Sta=316.2,331.2
XS Rating Curve= 0 ,0
Exp/Cntr=0.3,0.1

Type RM Length L Ch R = 1 ,1321.6  ,378.8,371.7,364.6
XS GIS Cut Line= 4
     1623809.229      298377.929     1624062.899      298384.239
     1624192.334      298429.643     1624393.912      298425.422
#Sta/Elev= 30
     9.8 1057.33    19.5 1049.08    48.8 1034.59    78.1 1018.12    87.8 1008.53
    97.6 1001.63   146.4  972.64   165.9  954.43   214.7   924.5   224.5  917.57
   234.2  908.11     244  900.53   253.7  896.94   273.3   896.8   283.1  895.74
     305  891.43   312.5  890.35     320  890.42   371.3  897.13   381.1  899.95
   390.9  906.14     401  921.53   411.1  929.69   461.5  960.45   471.6  971.97
   481.6  979.08   532.1 1008.92   542.1  1018.5   552.2 1024.58   592.5 1045.51
#Mann= 3 , 0 , 0
       0      .1       0     305    .045       0     320      .1       0
Bank Sta=305,320
XS Rating Curve= 0 ,0
Exp/Cntr=0.3,0.1

Type RM Length L Ch R = 1 ,949.9   ,214.2,218,221.7
XS GIS Cut Line= 3
     1623755.404      298757.869     1624211.331      298768.422
     1624464.623      298785.309
#Sta/Elev= 30
    10.1 1061.33    20.3 1055.91    30.4 1046.15    40.5 1039.43   101.3 1006.09
   111.5   996.5   121.6     990   172.3  963.89   182.4   954.9   192.6  948.72
   243.2   923.1   253.4  913.36   263.5  906.51   283.8   895.7     304  889.73
   344.6  888.15   377.6  883.42   385.1  882.69   392.6   883.3   395.2  883.52
   415.5  901.23   465.8  935.44   485.3  954.59   543.9  986.72   563.4 1002.46
     622 1034.09   631.8  1045.1   651.3 1057.27   690.4 1076.71   709.9 1089.22
#Mann= 3 , 0 , 0
       0      .1       0   377.6    .045       0   392.6      .1       0
Bank Sta=377.6,392.6
XS Rating Curve= 0 ,0
Exp/Cntr=0.3,0.1

Type RM Length L Ch R = 1 ,731.9   ,169.4,166.1,162.8
XS GIS Cut Line= 3
     1623775.456       298924.62     1623997.087      298955.226
     1624368.583      299025.937
#Sta/Elev= 30
     9.7 1046.56    19.5 1041.27    38.9 1025.28    87.5  999.24    97.3  992.61
     107  984.13   116.7  978.24   175.1  946.87   184.8  935.98   194.6  927.53
   223.7  905.07   243.6  894.92   263.5  882.84   273.5   878.9   285.9  876.48
   293.4  876.28   300.9  877.24   323.3  881.16   363.1  884.39     373  886.05
     383  890.05   402.9  902.74   412.8  915.61   452.6  943.62   462.6   949.3
   492.4  962.92   522.3  974.23   552.1   987.2     572 1001.21   601.9 1015.69
#Mann= 3 , 0 , 0
       0      .1       0   285.9    .045       0   300.9      .1       0
Bank Sta=285.9,300.9
XS Rating Curve= 0 ,0
Exp/Cntr=0.3,0.1

Type RM Length L Ch R = 1 ,565.8   ,262.2,271,279.8
XS GIS Cut Line= 3
     1623771.235      299120.921     1624119.512      299135.697
     1624375.971       299144.14
#Sta/Elev= 30
      10  1035.8    39.8 1020.06    49.8 1013.35    59.8 1003.89   109.6   976.9
   119.5  970.77   129.5  960.57   199.2  923.15   209.2  913.26     259   889.7
   268.9  883.99   278.9   874.4   281.3  873.89   288.8  872.29   296.3  873.45
   318.7   877.5   348.6  878.74   358.5  880.35   368.3  884.33   417.7  917.11
   437.4  937.17   447.3  943.34     467  953.03   486.8  960.45   496.6  965.24
   506.5   972.3   565.7  999.72   575.6 1006.93   585.5 1012.43   605.2 1021.14
#Mann= 3 , 0 , 0
       0      .1       0   281.3    .045       0   296.3      .1       0
Bank Sta=281.3,296.3
XS Rating Curve= 0 ,0
Exp/Cntr=0.3,0.1

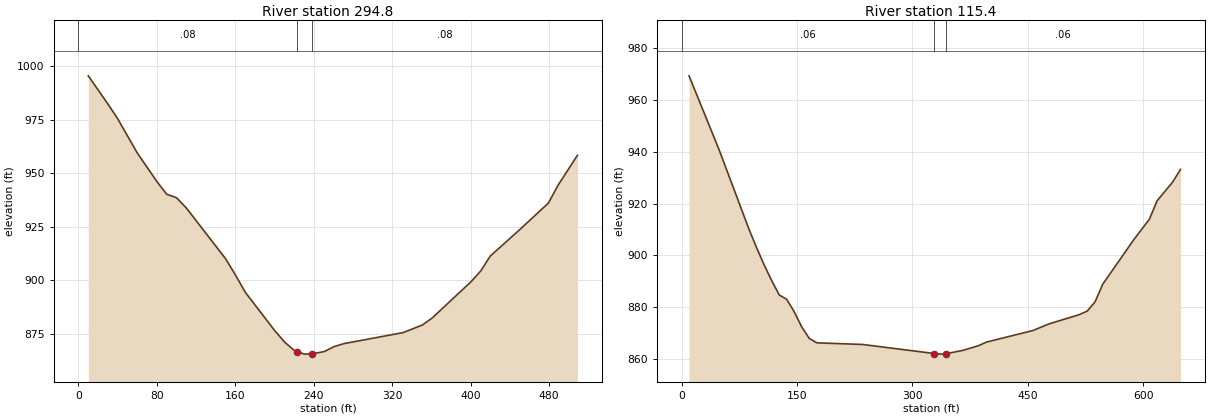
Type RM Length L Ch R = 1 ,294.8   ,173.4,179.4,185.5
XS GIS Cut Line= 4
     1623807.118      299241.235     1623952.761      299378.436
     1624054.078      299424.873     1624251.435       299418.54
#Sta/Elev= 30
      10  995.51      30  982.37      40  975.45      60  959.44      80   946.1
      90  940.18     100  938.55     110  933.78   150.1  910.01   160.1  902.48
   170.1  894.42   200.1  876.49   210.2  871.13   220.4  867.06     223  866.65
   230.5  865.46     238  865.56   250.7  866.66   260.9  869.01     271  870.39
   331.3  875.53     351  879.11   360.9  882.37   400.4  899.28   410.3  904.28
   420.1  911.31   449.8  923.49   479.4  936.07   489.3  944.43     509  958.38
#Mann= 3 , 0 , 0
       0     .08       0     223    .045       0     238     .08       0
Bank Sta=223,238
XS Rating Curve= 0 ,0
Exp/Cntr=0.3,0.1

Type RM Length L Ch R = 1 ,115.4   ,101.7,115.4,129
XS GIS Cut Line= 4
     1623781.788      299294.005     1623887.511      299469.867
     1624047.746      299607.454     1624273.598       299553.63
#Sta/Elev= 30
     9.8  969.22    48.9  940.71    87.9  909.98    97.7  902.94   107.5   896.3
   117.3  890.28     127   884.8   136.8   883.1   146.6  878.27   156.3  872.44
   166.1  868.05   175.9  866.34   235.4  865.71   328.4  862.23   335.9  861.99
   343.4  862.13   366.1  863.46   386.2  865.26   396.3  866.62   456.8  871.08
     477  873.56   517.3  877.23   527.4  878.57   537.5  882.08   547.6  888.93
     588  906.13   608.2  913.98   618.3   921.1   638.5  928.31   648.6  933.17
#Mann= 3 , 0 , 0
       0     .06       0   328.4    .045       0   343.4     .06       0
Bank Sta=328.4,343.4
XS Rating Curve= 0 ,0
Exp/Cntr=0.3,0.1

Chan Stop Cuts=-1
Use User Specified Reach Order=0